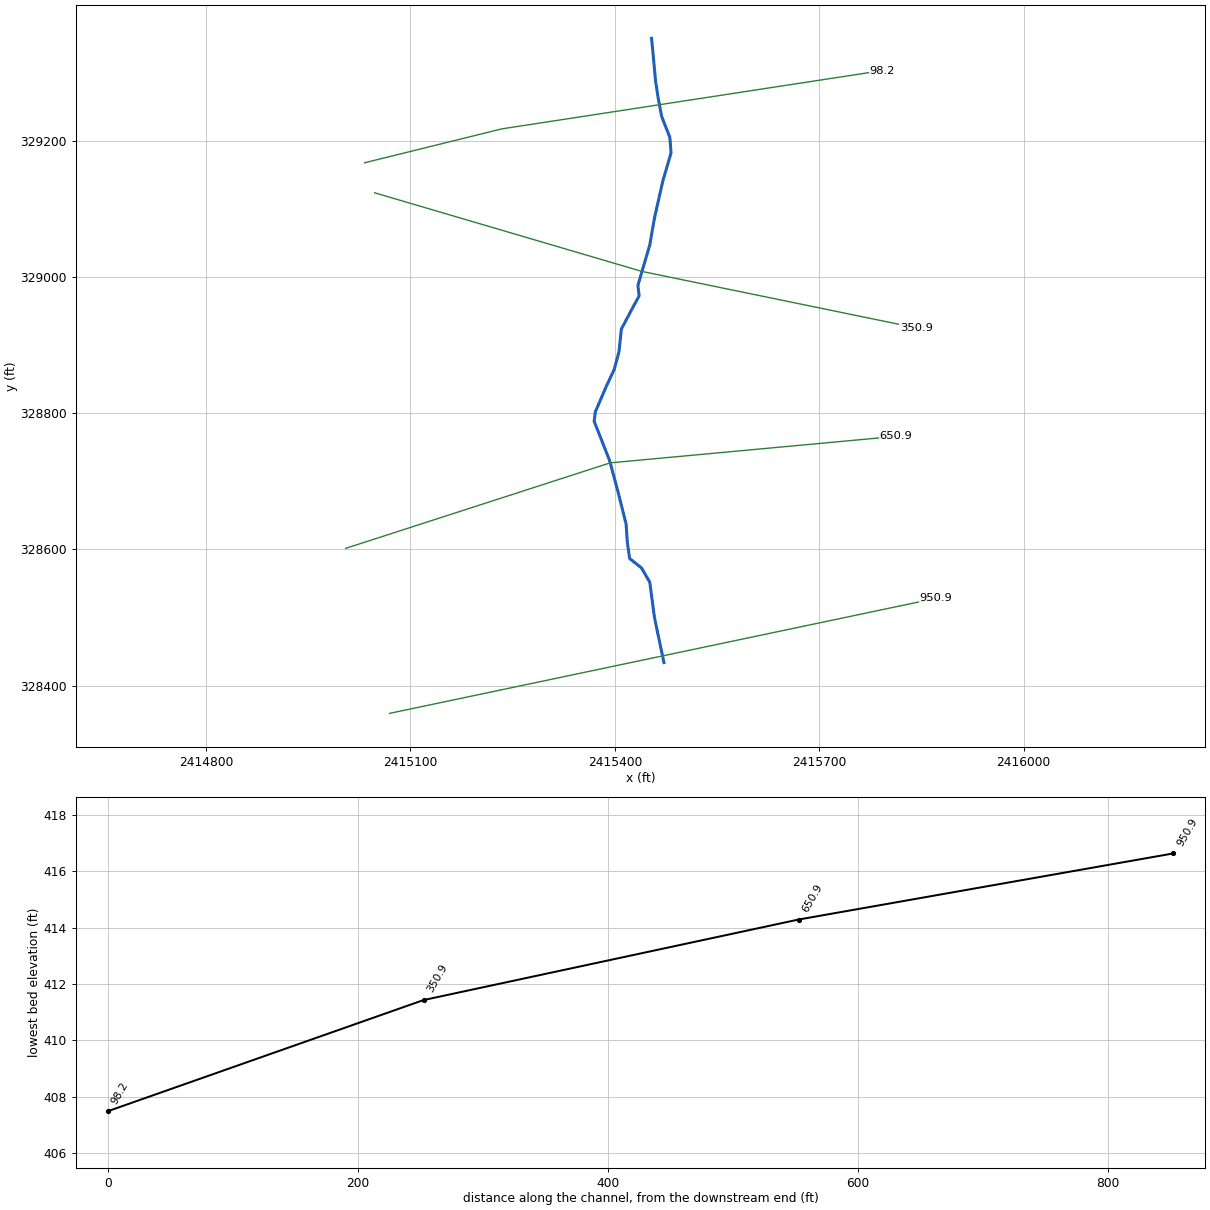
--- SHAWRNTRIB.prj (project) ---

Proj Title=SHAWRNTRIB
Current Plan=p01
Default Exp/Contr=0,0
English Units
Geom File=g01
Flow File=f01
Plan File=p01
BEGIN DESCRIPTION:
END DESCRIPTION:
DSS Export Rating Curves= 0
DSS Export Rating Curve Sorted= 0
DSS Export Volume Flow Curves= 0
DXF OffsetX= 0
DXF OffsetY= 0
DXF ScaleX= 0
DXF ScaleY= 0

--- SHAWRNTRIB.p01 (plan) ---

Plan Title=Floodplain
Program Version=4.00
Geom File=g01
Flow File=f01
K Sum by GR=0
Std Step Tol=0.01
Critical Tol=0.01
Num of Std Step Trials=20
Max Error Tol=0.3
Flow Tol Ratio=0.001
Split Flow NTrial=30
Split Flow Tol=0.02
Split Flow Ratio=0.02
Log Output Level=0
Friction Slope Method=1
Unsteady Friction Slope Method=2
Unsteady Bridges Friction Slope Method=1
Global Log Level=0
CheckData=False
Run HTab=0
Run UNet=0
Run PostProcess=0
UNET Theta=0
UNET Theta Warmup=0
UNET ZTol=0
UNET ZSATol=0
UNET MxIter=0
UNET MaxInSteps=0
UNET DtIC=0
UNET DtMin=0
UNET MaxCRTS=0
UNET WFStab=0
UNET SFStab=0
UNET WFX=0
UNET SFX=0
UNET DSS MLevel=0
UNET DZMax Abort=0
UNET Convert EG Bridges=0
UNET Use Existing IB Tables=0
UNET Froude Limit=0
UNET Froude Power=0
Write IC File=0
Echo Input=False
Echo Output=False
Write Detailed=0

--- SHAWRNTRIB.f01 (steady flow) ---

Flow Title=NFF Regression Equation
Program Version=4.00
Number of Profiles=1
Profile Names=P100yr
River Rch & RM=SHAWRNTRIB,Main      ,950.9
1046.333
River Rch & RM=SHAWRNTRIB,Main      ,98.2
1052.601
Boundary for River Rch & Prof#=SHAWRNTRIB,Main      ,1
Up Type=0
Dn Type=3
Dn Slope=0.010997

--- SHAWRNTRIB.g01 (geometry) ---

Geom Title=USGS 10m DEM
Program Version=4.10

River Reach=SHAWRNTRIB      ,Main
Reach XY= 28
     2415472.076      328433.965     2415458.187      328499.937
     2415451.242      328552.021      2415439.09      328572.854
     2415421.729      328586.743     2415418.256      328611.048
      2415416.52       328637.09     2415404.368      328685.701
     2415392.215       328730.84     2415369.645      328788.132
     2415371.381      328802.021     2415387.006      328838.479
     2415399.159      328864.521     2415406.103      328890.562
     2415409.576      328923.548     2415425.201      328953.062
     2415435.617       328972.16     2415433.881      328987.785
     2415442.562      329017.299     2415451.242      329046.812
     2415458.187      329086.743      2415470.34      329140.562
     2415482.492      329182.229     2415480.757      329204.799
     2415468.604      329236.049     2415463.395      329263.826
     2415459.923      329286.396     2415453.934       329350.33

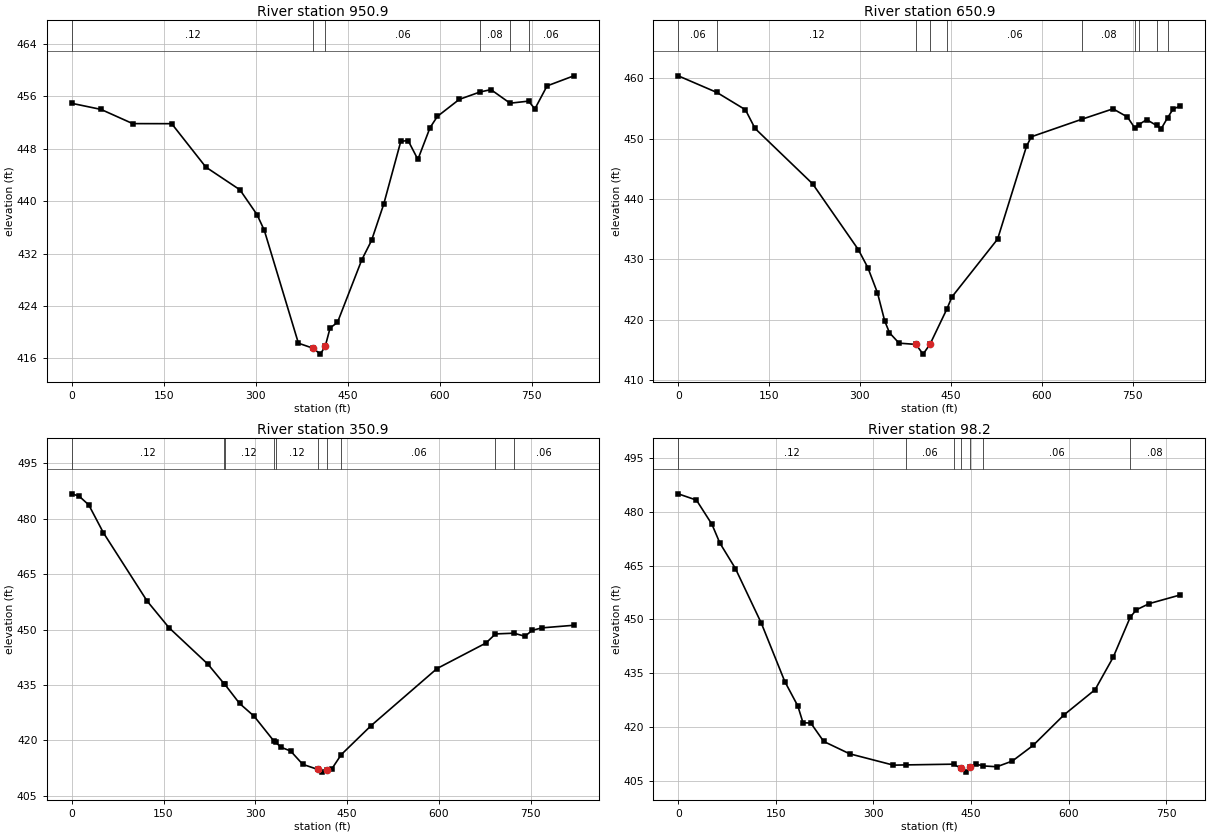
Type RM Length L Ch R = 1 ,950.9   ,297.3,300,294.3
XS GIS Cut Line= 3
     2415069.299       328359.39     2415470.016      328443.751
     2415870.732      328528.111
#Sta/Elev= 30
       0  454.95    47.7  454.02    99.4  451.85     163  451.84   218.7  445.21
   274.3  441.74   302.2  437.95   314.1  435.54   369.7  418.31   393.6  417.54
   405.5  416.64   413.5  417.85   421.4  420.64   433.4  421.48   473.1  431.05
     489     434   508.9  439.56   536.7  449.14   548.6  449.27   564.6  446.38
   584.4  451.23   596.4  452.95   632.1  455.55  666.11456.6874   683.8  457.04
  714.94454.9694   745.2455.2872   755.4  454.09   775.3  457.61     819  459.15
#Mann= 6 ,-1 , 0
       0     .12       0   393.6    .045       0   413.5     .06       0
  666.11     .08       0  714.94    .016       0   745.2     .06       0
Bank Sta=393.6,413.5
XS Rating Curve= 0 ,0
Exp/Cntr=0.3,0.1

Type RM Length L Ch R = 1 ,650.9   ,322.6,300,288.8
XS GIS Cut Line= 3
     2415004.875      328601.634     2415393.208      328727.152
      2415812.13      328765.985
#Sta/Elev= 30
       0   460.4    63.9  457.64   110.9  454.78   126.8  451.68   221.9   442.5
   297.2  431.62     313  428.62   328.9  424.44   340.8   419.8   348.7  417.83
   364.5  416.11   392.3   415.9   404.2  414.29   415.6  415.92  443.68421.8111
   451.8  423.77   527.2  433.35   574.8   448.7   582.8   450.3  666.76453.2233
   717.7  454.93   741.5  453.58  753.77 451.742  759.98452.2986   773.3  453.14
  789.67452.1703   797.1  451.61  807.77453.4494   816.9  454.89   828.8   455.4
#Mann= 10 ,-1 , 0
       0     .06       0    63.9     .12       0   392.3    .045       0
   415.6     .12       0  443.68     .06       0  666.76     .08       0
  753.77     .06       0  759.98    .016       0  789.67     .06       0
  807.77     .12       0
Bank Sta=392.3,415.6
XS Rating Curve= 0 ,0
Exp/Cntr=0.3,0.1

Type RM Length L Ch R = 1 ,350.9   ,236,252.7,266.2
XS GIS Cut Line= 3
     2415047.291      329123.601     2415439.867      329008.136
     2415842.613      328925.309
#Sta/Elev= 30
       0   486.7    11.9  486.08    27.8   483.7    51.6  476.19   123.2  457.68
   158.9  450.49   222.5  440.62  248.79435.3589  250.08435.1719   274.1  430.02
     298  426.54  329.95419.9012  333.43419.4639   341.7  418.17   357.6  417.14
   377.4  413.54   401.7  412.18   409.2  411.43   416.7  411.97   425.2  412.38
  440.41416.1778     489  423.99   596.8  439.44   676.7  446.34  692.37448.8081
   722.4 449.006   740.5  448.18   752.5  449.79   768.5  450.45   820.4  451.15
#Mann= 10 ,-1 , 0
       0     .12       0  248.79     .06       0  250.08     .12       0
  329.95     .06       0  333.43     .12       0   401.7    .045       0
   416.7     .12       0  440.41     .06       0  692.37    .016       0
   722.4     .06       0
Bank Sta=401.7,416.7
XS Rating Curve= 0 ,0
Exp/Cntr=0.3,0.1

Type RM Length L Ch R = 1 ,98.2    ,100.4,98.2,96
XS GIS Cut Line= 3
     2415032.536      329167.629     2415234.221      329217.457
     2415791.819      329302.876
#Sta/Elev= 30
       0     485      28  483.25    51.9  476.48    63.9  471.32    87.9  464.19
   127.8  448.94   163.8  432.72   183.8  425.92   191.8  421.23   203.8  421.15
   223.6  416.03   263.4  412.59   330.9  409.42  350.33 409.493  423.45409.6976
   434.2  408.56   442.1  407.48   449.2  408.88     458  409.67  469.22409.2049
   489.8  408.98   513.6  410.57   545.4  414.91   593.1  423.44   640.8  430.45
   668.6  439.47   694.9450.6675   704.3   452.7   724.2  454.43   771.8  456.84
#Mann= 7 ,-1 , 0
       0     .12       0  350.33     .06       0  423.45     .12       0
   434.2    .045       0   449.2     .12       0  469.22     .06       0
   694.9     .08       0
Bank Sta=434.2,449.2
XS Rating Curve= 0 ,0
Exp/Cntr=0.3,0.1

Chan Stop Cuts=-1
Use User Specified Reach Order=0
Composite Channel Slope=5